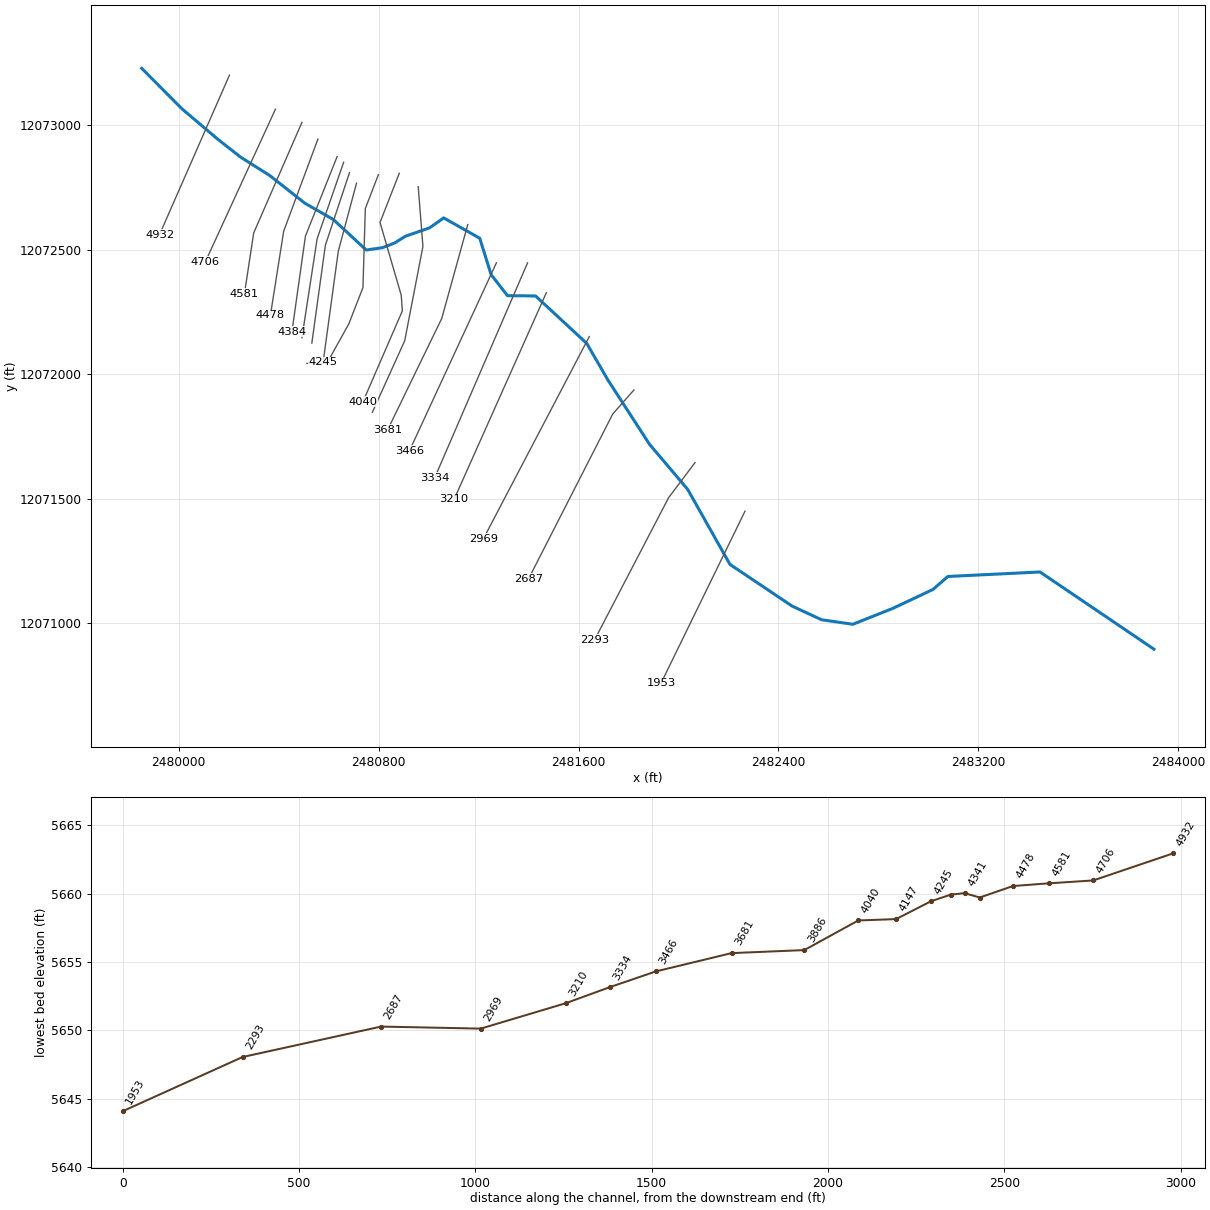
--- GilaRiverBridge.prj (project) ---

Proj Title=Gila River Bridge
Current Plan=p07
Default Exp/Contr=0.3,0.1
English Units
Geom File=g16
Flow File=f05
Plan File=p07
Y Axis Title=Elevation
X Axis Title(PF)=Main Channel Distance
X Axis Title(XS)=Station
BEGIN DESCRIPTION:
END DESCRIPTION:
DSS Export Rating Curves= 0
DSS Export Rating Curve Sorted= 0
DSS Export Volume Flow Curves= 0
DXF Filename=..\WMS HEC-RAS 010612.
DXF OffsetX= 0
DXF OffsetY= 0
DXF ScaleX= 1
DXF ScaleY= 10

--- GilaRiverBridge.p07 (plan) ---

Plan Title=Plan 07
Program Version=4.10
Short Identifier=Plan 07
Geom File=g16
Flow File=f05
Mixed Flow
K Sum by GR= 0
Std Step Tol= 0.01
Critical Tol= 0.01
Num of Std Step Trials= 20
Max Error Tol= 0.3
Flow Tol Ratio= 0.001
Split Flow NTrial= 30
Split Flow Tol= 0.02
Split Flow Ratio= 0.02
Log Output Level= 0
Friction Slope Method= 1
Unsteady Friction Slope Method= 2
Unsteady Bridges Friction Slope Method= 1
Calc Critical at every XS
Parabolic Critical Depth
Global Vel Dist= 0 , 0 , 0
Global Log Level= 0
CheckData=True
Encroach Param=-1 ,0,0, 0
BEGIN DESCRIPTION:
NM Gila River Bridge - Preliminary Hydraulic Analysis for bridge sizing.   All XS cut from 2012 Aerial mapping.
210 ft  3-span bridge with 2H:1V Sloping Abutments
END DESCRIPTION:
Computation Interval=1HOUR
Output Interval=1HOUR
Run HTab= 0
Run UNet= 0
Run PostProcess= 0
Run WQNet= 0
UNET Theta= 1
UNET Theta Warmup= 1
UNET ZTol= 0.02
UNET ZSATol= 0.05
UNET MxIter= 20
UNET MaxInSteps= 0
UNET DtIC= 0
UNET DtMin= 0
UNET MaxCRTS= 20
UNET WFStab= 2
UNET SFStab= 1
UNET WFX= 1
UNET SFX= 1
UNET DSS MLevel= 4
UNET DZMax Abort= 100
UNET Convert EG Bridges= 0
UNET Use Existing IB Tables=-1
UNET Froude Reduction=False
UNET Froude Limit= 1
UNET Froude Power= 10
UNET Time Slicing=0,0, 5
UNET Junction Losses=0
Instantaneous Interval=1HOUR
Write IC File= 0
Write IC File at Sim End=0
Echo Input=False
Echo Parameters=False
Echo Output=False
Write Detailed= 0
WQ AD Non Conservative
WQ ULTIMATE=-1
WQ Max Comp Step=1HOUR
WQ Output Interval=15MIN
WQ Output Selected Increments= 0
WQ Output face flow=0
WQ Output face velocity=0
WQ Output face area=0
WQ Output face dispersion=0
WQ Output cell volume=0
WQ Output cell surface area=0
WQ Output cell continuity=0
WQ Output cumulative cell continuity=0
WQ Output face conc=0
WQ Output face dconc_dx=0
WQ Output face courant=0
WQ Output face peclet=0
WQ Output face adv mass=0
WQ Output face disp mass=0
WQ Output cell mass=0
WQ Output cell source sink temp=0
WQ Output cell source sink nsm=0
WQ Output MaxMinRange=-1
WQ Daily Max Min Mean=-1
WQ Daily Range=0
WQ Daily Time=0
WQ Create Restart=0
WQ Fixed Restart=0
WQ System Summary=0
WQ Use Fixed Temperature=0
Sorting and Armoring Iterations= 10
XS Update Threshold= 0.02
Hydraulics Update Threshold= 0.02
Energy Slope Method= 1
Volume Change Method= 0
XS Weighting Method= 0
Number of US Weighted Cross Sections= 1
Number of DS Weighted Cross Sections= 1
Upstream XS Weight=0.25
Main XS Weight=0.5
Downstream XS Weight=0.25
Number of DS XS's Weighted with US Boundary= 1
Upstream Boundary Weight= 1
Weight of XSs Associated with US Boundary= 0
Number of US XS's Weighted with DS Boundary= 1
Downstream Boundary Weight= 0.5
Weight of XSs Associated with DS Boundary= 0.5
Sediment Output Level= 4
Mass or Volume Output= 0
Output Increment Type= 1
Profile and TS Output Increment= 10
XS Output Flag= 0
XS Output Increment= 10
Disregard all LS=0
Disregard all Conn=0
Disregard all Breaches=0
Disregard all Pumps=0

--- GilaRiverBridge.f05 (steady flow) ---

Flow Title=SteadyFlowData
Program Version=4.10
Number of Profiles= 1
Profile Names=100-yr
River Rch & RM=Gila River,West Fork       ,4932
   14344
River Rch & RM=Gila River,West Fork       ,4147
   12744
Boundary for River Rch & Prof#=Gila River,West Fork       , 1
Up Type= 3
Up Slope=0.001
Dn Type= 3
Dn Slope=0.006
DSS Import GetInterval= 0
DSS Import GetPeak= 0
DSS Import FillOption= 0

--- GilaRiverBridge.g16 (geometry) ---

Geom Title=195 ft 3-span  w 2:1 sloping abuts
Program Version=4.10

River Reach=Gila River      ,West Fork
Reach XY= 30
        2479852.       12073229.      2480013.25      12073066.2
      2480156.93     12072943.87      2480248.19     12072872.03
      2480364.68     12072798.25      2480504.48     12072687.58
      2480619.03     12072621.57      2480750.49     12072499.24
       2480815.1     12072508.74      2480864.51     12072527.74
      2480906.32     12072554.35      2481004.19     12072588.56
      2481060.26     12072628.47      2481204.69     12072546.75
       2481250.3     12072400.42      2481315.86     12072315.85
      2481427.99      12072314.9      2481633.23     12072123.91
      2481716.85     12071978.52      2481884.08     12071719.12
      2482037.07     12071537.63       2482206.2     12071236.41
        2482455.       12071069.      2482572.98     12071014.06
      2482698.41     12070996.01      2482859.95     12071060.62
      2483018.63     12071135.69      2483078.49     12071187.95
      2483447.17     12071206.01        2483903.       12070896.

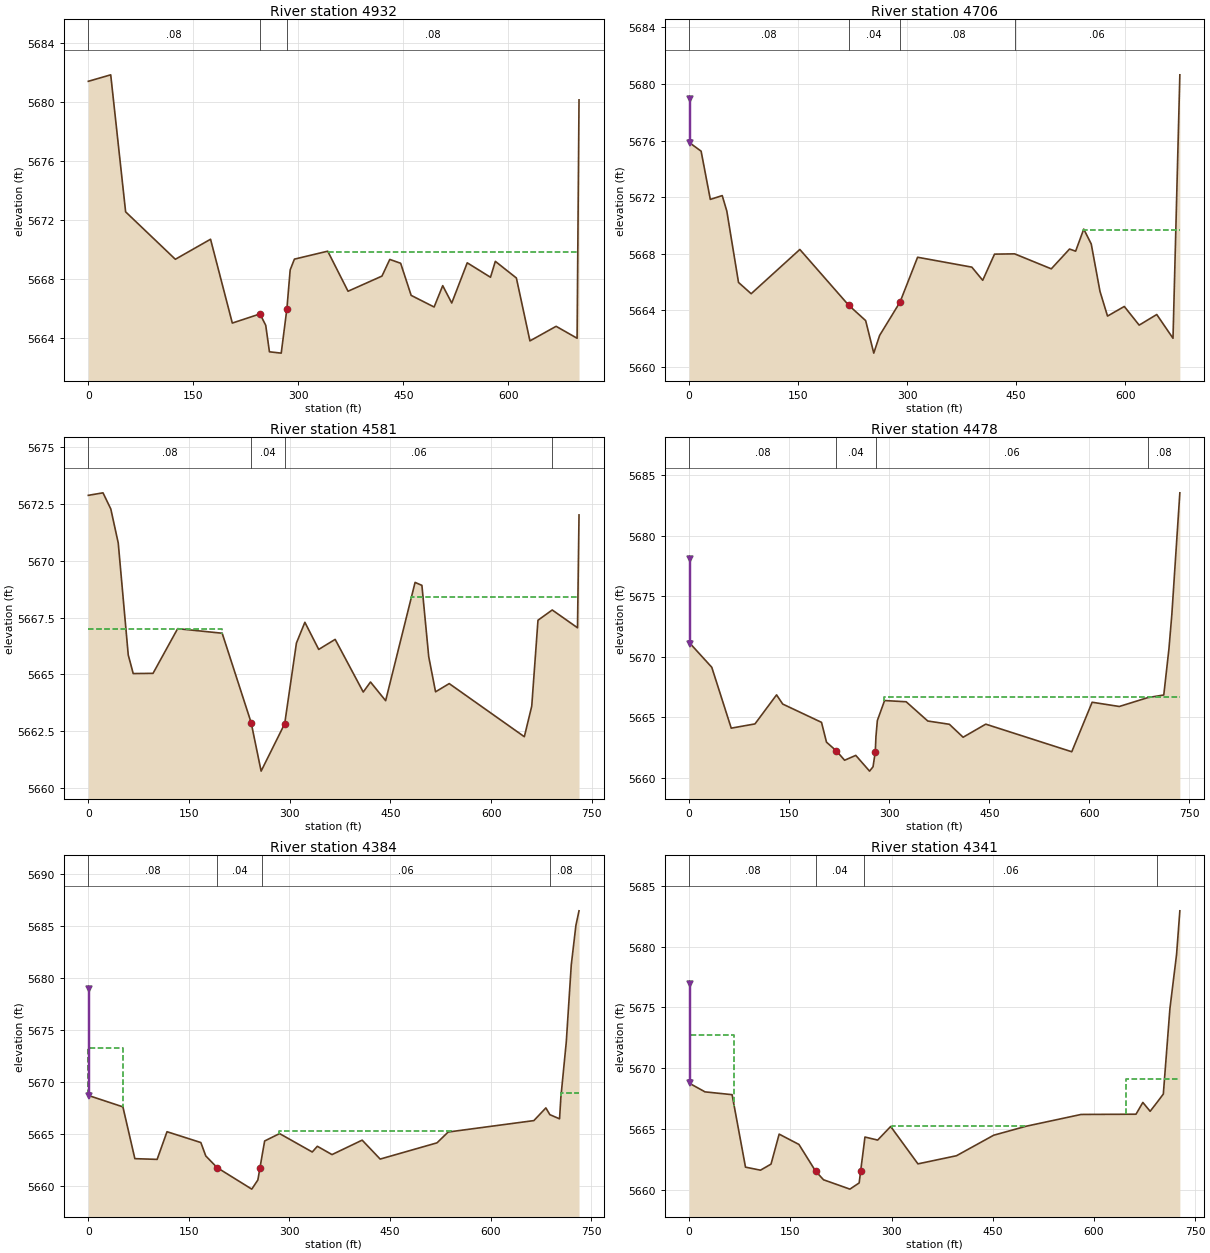
Type RM Length L Ch R = 1 ,4932    ,224.85,226.3,226.3
XS GIS Cut Line= 6
        2480203.       12073202.      2480063.54     12072882.75
      2480030.69     12072807.52      2480026.25     12072797.38
      2480005.32     12072749.44        2479923.       12072561.
#Sta/Elev= 30
       0  5681.4   31.98 5681.84   53.27 5672.54  124.29 5669.32  174.55 5670.68
  205.64 5664.99  245.13 5665.61  253.36 5664.84  258.66 5663.04   275.5 5662.95
  283.62 5665.97  288.28  5668.6  294.33 5669.33  341.92 5669.87  370.92 5667.15
   419.4 5668.18  430.52 5669.31  446.05 5669.05  461.07 5666.87  493.85 5666.08
  506.15 5667.53  519.02 5666.35  541.16 5669.08  574.37  5668.1  581.27 5669.18
  611.33 5668.05   630.7 5663.78  668.09 5664.77  698.03 5663.96   700.8 5680.14
#Mann= 3 ,-1 , 0
       0     .08       0  245.13     .04       0  283.62     .08       0
#XS Ineff= 2 , 0
                    5669  342.59         5669.82
Permanent Ineff=
       F       F
Bank Sta=245.13,283.62
XS Rating Curve= 0 ,0
Exp/Cntr=0.3,0.1

Type RM Length L Ch R = 1 ,4706    ,126.3,125.16,124.26
XS GIS Cut Line= 6
        2480387.       12073065.        2480384.     12073058.46
      2480382.89     12073056.01      2480335.82     12072953.18
      2480330.77     12072942.12        2480106.       12072451.
#Sta/Elev= 30
       0 5675.87   16.47 5675.25   29.13 5671.84   45.52 5672.11   51.85 5671.01
   67.92 5665.97   85.33 5665.17  152.31  5668.3  219.29 5664.37  242.88 5663.27
  254.05 5660.97  262.08 5662.22  290.18 5664.58  314.35 5667.75  389.03 5667.05
  403.96 5666.12  420.21 5667.97   447.9 5667.99  498.35 5666.93  523.44 5668.33
  531.84 5668.18     543 5669.74  553.31 5668.69  565.33 5665.34  575.71 5663.59
  598.81 5664.27  619.26 5662.95  643.46  5663.7  665.83 5662.02  675.25 5680.65
#Mann= 4 ,-1 , 0
       0     .08       0  219.29     .04       0  290.18     .08       0
   447.9     .06       0
Levee=-1,1.59,5678.95,0,,,,
#XS Ineff= 2 , 0
                    5669  542.01         5669.67
Permanent Ineff=
       F       F
Bank Sta=219.29,290.18
XS Rating Curve= 0 ,0
Exp/Cntr=0.3,0.1

Type RM Length L Ch R = 1 ,4581    ,99.99,102.51,102.63
XS GIS Cut Line= 6
        2480493.       12073012.      2480356.19     12072697.28
      2480351.79     12072687.13      2480307.47     12072585.17
        2480300.       12072568.        2480263.       12072324.
#Sta/Elev= 30
       0 5672.86   21.87 5672.97    33.5 5672.26   44.56 5670.77   59.46 5665.86
   66.88 5665.04   96.39 5665.05  133.04 5667.01  199.39 5666.81  242.51 5662.89
  257.39 5660.76   292.5 5662.84  309.99 5666.38  322.57 5667.29  343.17  5666.1
  367.68 5666.54  409.53 5664.23   420.3 5664.67  442.86 5663.85  486.72 5669.04
  496.89 5668.91  507.06 5665.78  517.23 5664.24  537.57  5664.6  649.45 5662.27
  660.49 5663.61  669.79 5667.38  691.01 5667.83  728.66 5667.05  730.92    5672
#Mann= 4 ,-1 , 0
       0     .08       0  242.51     .04       0   292.5     .06       0
  691.01     .08       0
#XS Ineff= 2 , 0
          199.76    5667  480.56         5668.42
Permanent Ineff=
       F       F
Bank Sta=242.51,292.5
XS Rating Curve= 0 ,0
Exp/Cntr=0.3,0.1

Type RM Length L Ch R = 1 ,4478    ,93.26,94,91.66
XS GIS Cut Line= 6
        2480557.       12072945.       2480551.1     12072929.05
      2480548.97     12072923.33      2480545.23      12072913.2
        2480420.       12072575.        2480367.       12072238.
#Sta/Elev= 30
       0 5671.19   33.91 5669.14    63.1 5664.11   98.67 5664.46  131.06 5666.86
  140.28  5666.1  198.43 5664.59  205.94 5662.95  220.79 5662.23  233.07 5661.46
   249.8 5661.86  270.49 5660.56   275.7 5660.92  279.09 5662.17  280.05 5663.41
  282.18 5664.74  292.98 5666.39  325.36 5666.29  357.75  5664.7  390.13 5664.43
  410.74 5663.36   444.7 5664.44  573.63 5662.16  604.18 5666.25   644.9  5665.9
  687.49 5666.63  711.59 5666.85  719.37 5670.68  723.66 5673.49  735.69 5683.55
#Mann= 4 ,-1 , 0
       0     .08       0  220.79     .04       0  280.05     .06       0
  687.49     .08       0
Levee=-1,1.82,5678.06,0,,,,
#XS Ineff= 2 , 0
          129.63 5666.75  292.59          5666.7
Permanent Ineff=
       F       F
Bank Sta=220.79,279.09
XS Rating Curve= 0 ,0
Exp/Cntr=0.5,0.3

Type RM Length L Ch R = 1 ,4384    ,40.26,43.27,45.65
XS GIS Cut Line= 6
        2480634.       12072875.      2480620.37     12072840.64
      2480604.07      12072799.6      2480596.14     12072779.59
        2480507.       12072555.        2480453.       12072171.
#Sta/Elev= 30
       0 5668.73   51.57 5667.63   69.43 5662.65  102.64 5662.58  117.38 5665.24
  167.86  5664.2  175.24 5662.91  192.11 5661.79  243.83 5659.72  252.92  5660.6
  256.15 5661.79  259.33 5662.99  263.07 5664.35  285.33 5665.06   334.1 5663.29
  341.66 5663.84  363.56 5663.04  408.52 5664.43  435.37 5662.61  520.19 5664.17
  536.83 5665.21  664.72 5666.31   682.6 5667.53  688.55 5666.88  703.01 5666.48
  704.98 5668.55  713.06 5673.88   720.5 5681.28  727.43 5685.09  732.06 5686.48
#Mann= 4 ,-1 , 0
       0     .08       0  192.11     .04       0  259.33     .06       0
  688.55     .08       0
Levee=-1,0.91,5678.96,0,,,,
#XS Ineff= 3 ,-1
       0   51.645673.308  284.26  543.52 5665.35  705.16  732.06    5669
Permanent Ineff=
       F       F       F
Bank Sta=192.11,256.15
XS Rating Curve= 0 ,0
Exp/Cntr=0.3,0.3

Type RM Length L Ch R = 1 ,4341    ,37.86,39.17,40.73
XS GIS Cut Line= 6
        2480660.       12072852.      2480575.24      12072606.5
      2480574.99     12072605.81      2480574.99     12072605.78
        2480554.       12072545.        2480493.       12072147.
#Sta/Elev= 30
       0 5668.77   23.54 5668.05   63.66 5667.82   83.54 5661.85  105.76  5661.6
  121.38  5662.1  133.43 5664.57  162.73 5663.72  187.34 5661.53  199.18 5660.81
  238.32 5660.04  252.05 5660.55  254.24 5661.53  259.24 5663.71  260.59 5664.33
  279.46 5664.08  298.75  5665.2  339.18 5662.12  396.31 5662.79  451.47 5664.48
  499.64 5665.22  581.03 5666.19  662.42 5666.21  672.59 5667.18  683.38 5666.45
  693.15 5667.15  702.94 5667.87  712.69  5674.9  722.59 5679.38  727.43 5682.96
#Mann= 4 ,-1 , 0
       0     .08       0  187.34     .04       0  259.24     .06       0
  693.15     .08       0
Levee=-1,0.91,5676.91,0,,,,
#XS Ineff= 3 ,-1
     .91   66.645672.718  300.93  500.93 5665.26  648.03  727.43 5669.15
Permanent Ineff=
       F       F       F
Bank Sta=187.34,254.24
XS Rating Curve= 0 ,0
Exp/Cntr=0.5,0.3

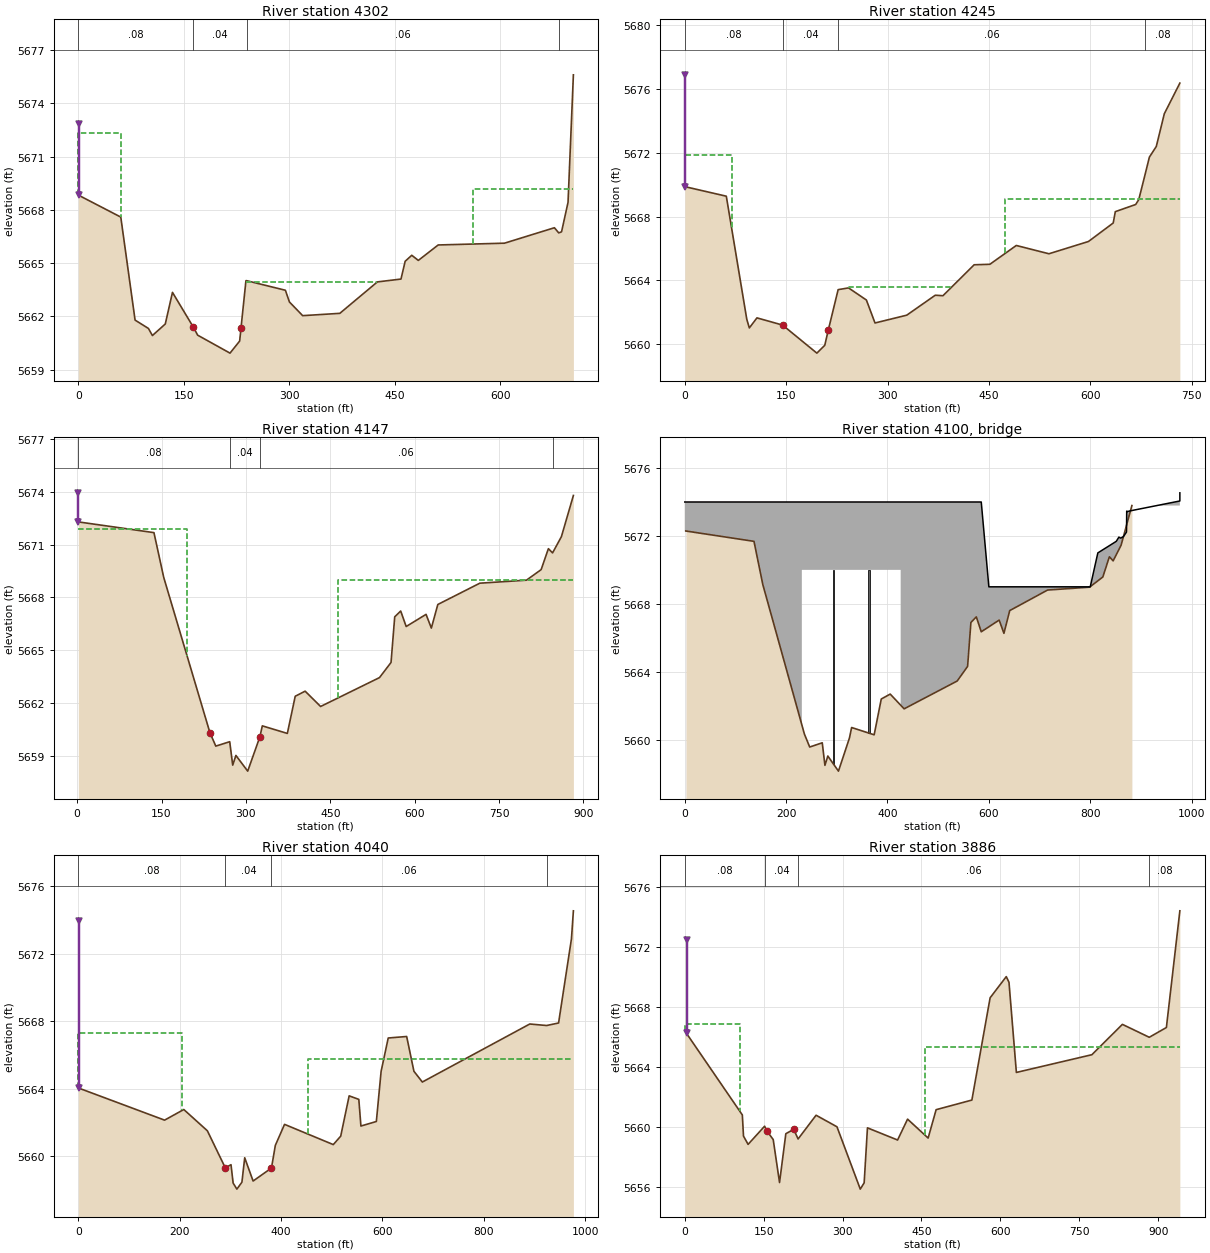
Type RM Length L Ch R = 1 ,4302    ,64.8,56.44,57.12
XS GIS Cut Line= 6
       2480683.3       12072810.      2480635.57     12072665.74
      2480594.41     12072541.29      2480589.03     12072525.06
       2480586.8      12072518.3       2480532.7      12072125.5
#Sta/Elev= 30
       0 5668.83    60.4 5667.59   80.72 5661.79   99.69 5661.32  105.36 5660.92
  123.65 5661.57  133.87 5663.35  163.44  5661.4  169.72 5660.94  215.66 5659.93
  229.38 5660.61   231.3 5661.35  238.31 5664.01  239.14 5664.01  294.38 5663.47
  300.13 5662.81  318.94 5662.04  371.74 5662.17  425.13 5663.94  458.69  5664.1
  464.61  5665.1  474.02 5665.44  483.35 5665.15  511.58 5666.02  605.76 5666.12
  676.78 5666.99  682.94  5666.7  686.92 5666.76  696.14 5668.42  703.76  5675.6
#Mann= 4 ,-1 , 0
       0     .08       0  163.44     .04       0  239.14     .06       0
  682.94     .08       0
Levee=-1,0.91,5672.82,0,,,,
#XS Ineff= 3 ,-1
   -2.73   60.185672.323  238.89     425 5663.96  561.05  703.76 5669.18
Permanent Ineff=
       F       F       F
Bank Sta=163.44,231.3
XS Rating Curve= 0 ,0
Exp/Cntr=0.5,0.3

Type RM Length L Ch R = 1 ,4245    ,116.62,98.34,127
XS GIS Cut Line= 6
       2480711.5      12072767.7      2480688.11     12072680.12
      2480687.81     12072679.04      2480678.79     12072645.23
       2480638.6      12072494.8 2480577.869745312072048.9481304
#Sta/Elev= 30
       0 5669.88   61.46 5669.28   91.77 5661.56   95.53 5661.02  106.81 5661.65
  144.68  5661.2  195.42 5659.44  207.13 5659.93  212.19 5660.86  226.91 5663.42
  242.28 5663.53   268.7 5662.77  281.45 5661.33  328.43 5661.82  370.59 5663.07
  381.99 5663.04  428.13 5664.98  451.38 5665.01  490.47 5666.19  538.75 5665.67
  597.24 5666.44  633.87  5667.6  636.94 5668.31  667.08 5668.76  671.61 5669.06
   680.7 5670.59  687.36 5671.73   697.6  5672.4  709.45 5674.45  732.44 5676.37
#Mann= 4 ,-1 , 0
       0     .08       0  144.68     .04       0  226.91     .06       0
   680.7     .08       0
Levee=-1,0.91,5676.89,0,,,,
#XS Ineff= 3 ,-1
     .91   69.455671.872  242.59  392.59 5663.56  474.07  732.44 5669.11
Permanent Ineff=
       F       F       F
Bank Sta=144.68,212.19
XS Rating Curve= 0 ,0
Exp/Cntr=0.5,0.3

Type RM Length L Ch R = 1 ,4147    ,98.15,107.29,195.36
XS GIS Cut Line= 6
        2480799.       12072802.      2480746.74     12072665.93
      2480737.27     12072348.65       2480680.9      12072203.1
 2480592.7095656 12072043.829216 2480512.7095656 12072043.829216
#Sta/Elev= 30
    2.08 5672.29  136.57 5671.68  153.94 5669.14  236.11 5660.32  246.53 5659.56
  271.27 5659.81  276.57 5658.48  282.29 5659.03  303.25 5658.14  324.91 5660.09
  329.23 5660.71   373.7 5660.28  387.71 5662.39  405.33 5662.68  432.84 5661.81
  537.54 5663.45  558.05 5664.31  564.59  5666.9  575.23 5667.23  584.96 5666.35
  620.31 5667.04  629.72 5666.26   641.2  5667.6  715.88 5668.81  798.74 5668.98
  824.88 5669.58  837.77 5670.77  845.21 5670.53  860.89 5671.45  882.22 5673.79
#Mann= 4 ,-1 , 0
    2.08     .08       0  271.27     .04       0  324.91     .06       0
  845.21     .08       0
Levee=-1,2.28,5673.94,0,,,,
#XS Ineff= 2 , 0
       0  195.68 5671.87     463       0    5669
Permanent Ineff=
       F       F
Bank Sta=236.11,324.91
XS Rating Curve= 0 ,0
Exp/Cntr=0.5,0.3

Type RM Length L Ch R = 3 ,4100    ,,,
Bridge Culvert--1,0,-1,-1, 0
Deck Dist Width WeirC Skew NumUp NumDn MinLoCord MaxHiCord MaxSubmerge Is_Ogee
40,30,3,0, 64, 64, 5667.5, , 0.98, 0, 1.5,1.5,,
       0     145  145.54  145.67     231     426  480.14  514.22  578.49     585
     600  605.56  607.61  609.66  615.12  615.57  617.82   620.5  626.85  628.19
  632.28  636.01  638.01  647.06  647.52  648.51  652.06  663.24  663.84  667.27
  674.71  675.64  675.71  676.63  676.77  686.18  689.39  702.86  706.26  737.94
  740.02  740.09  741.04  741.15  765.16  768.64  771.75  787.64  796.13  796.57
  796.77  796.85     800     815   851.3  856.57  860.06  865.46  871.59  871.95
  872.24     881  976.84  976.84
    5674    5674    5674    5674    5674    5674    5674    5674    5674    5674
    5669    5669    5669    5669    5669    5669    5669    5669    5669    5669
    5669    5669    5669    5669    5669    5669    5669    5669    5669    5669
    5669    5669    5669    5669    5669    5669    5669    5669    5669    5669
    5669    5669    5669    5669    5669    5669    5669    5669    5669    5669
    5669    5669    5669    5671 5671.68 5671.93 5671.87 5671.96 5672.23 5673.46
 5673.43 5673.49 5674.06 5674.54
                                    5670    5670
                                                                                
                                                                                
                                                                                
                                                                                
                                                                                
                                
       0     145  145.54  145.67     231     426  480.14  514.22  578.49     585
     600  605.56  607.61  609.66  615.12  615.57  617.82   620.5  626.85  628.19
  632.28  636.01  638.01  647.06  647.52  648.51  652.06  663.24  663.84  667.27
  674.71  675.64  675.71  676.63  676.77  686.18  689.39  702.86  706.26  737.94
  740.02  740.09  741.04  741.15  765.16  768.64  771.75  787.64  796.13  796.57
  796.77  796.85     800     815   851.3  856.57  860.06  865.46  871.59  871.95
  872.24     881  976.84  976.84
    5674    5674    5674    5674    5674    5674    5674    5674    5674    5674
    5669    5669    5669    5669    5669    5669    5669    5669    5669    5669
    5669    5669    5669    5669    5669    5669    5669    5669    5669    5669
    5669    5669    5669    5669    5669    5669    5669    5669    5669    5669
    5669    5669    5669    5669    5669    5669    5669    5669    5669    5669
    5669    5669    5669    5671 5671.68 5671.93 5671.87 5671.96 5672.23 5673.46
 5673.43 5673.49 5674.06 5674.54
                                    5670    5670
                                                                                
                                                                                
                                                                                
                                                                                
                                                                                
                                
Pier Skew, UpSta & Num, DnSta & Num=  ,293.5, 2 ,293.5, 2 , 0 , 0 , 0 ,,
       3       3
    5600    5673
       3       3
    5600    5673
Pier Skew, UpSta & Num, DnSta & Num=  ,363.5, 2 ,363.5, 2 , 0 , 0 , 0 ,,
       3       3
    5600    5673
       3       3
    5600    5673
Abutment Skew #Up #Dn= , 4 , 4
     231     233     251     251
    5668    5668    5659    5600
     231     233     251     251
    5668    5668    5659    5600
Abutment Skew #Up #Dn= , 4 , 4
     406     406     424     426
    5600    5659    5668    5668
     406     406     424     426
    5600    5659    5668    5668
BR Coef=-1 , 0 , 0 ,, 0 ,,,0.8,0,,0,
WSPro=,,,, 1 ,,,, 0 ,,,, 0 ,,,,-1 ,-1 ,-1 , 0 , 0 , 0 , 0 , 0
BC Design=,, 0 ,, 0 ,,,,,,
BC Use User HTab Curves=0
BC User HTab FreeFlow(D)= 0

Type RM Length L Ch R = 1 ,4040    ,183.24,153.16,144.08
XS GIS Cut Line= 6
      2480882.69     12072807.72       2480862.6      12072756.2
       2480805.6      12072610.1       2480890.3      12072318.4
        2480895.      12072254.9       2480737.4      12071890.2
#Sta/Elev= 30
       0 5664.04  170.27 5662.13  208.18 5662.76  254.66  5661.5  290.05  5659.3
  301.28 5659.49  305.52  5658.4  312.88 5658.04  322.83 5658.45  328.34  5659.9
   344.9 5658.52  381.12 5659.29  388.73 5660.63  406.92 5661.88   503.1 5660.68
  517.75 5661.18  534.42 5663.57  553.48 5663.36  557.62 5661.78  588.07 5662.05
  597.46 5665.02   611.5    5667  647.89 5667.09  662.18 5665.03  678.78 5664.39
   890.8 5667.83  924.01 5667.74  947.61 5667.89  973.01 5672.88  976.84 5674.54
#Mann= 4 ,-1 , 0
       0     .08       0  290.05     .04       0  381.12     .06       0
  924.01     .08       0
Levee=-1,1.14,5673.96,0,,,,
#XS Ineff= 2 , 0
       0  204.78 5667.32  453.92       0 5665.75
Permanent Ineff=
       F       F
Bank Sta=290.05,381.12
XS Rating Curve= 0 ,0
Exp/Cntr=0.5,0.3

Type RM Length L Ch R = 1 ,3886    ,247.05,205.9,142
XS GIS Cut Line= 6
       2480958.5      12072753.6       2480977.3      12072513.6
       2480904.4      12072134.9      2480849.82     12072013.86
      2480847.84     12072009.44        2480775.      12071847.9
#Sta/Elev= 30
       0 5666.41  109.46 5660.81  111.65  5659.4  120.41 5658.85  151.82 5660.06
  156.19 5659.74  168.16 5659.17  180.18 5656.31  192.14 5659.56  207.09 5659.85
  215.46 5659.21  249.65 5660.79  289.36 5660.02  333.67 5655.87  341.07 5656.29
  347.31 5659.95   404.6 5659.14  423.57 5660.53  462.66 5659.27  477.86 5661.16
  545.82  5661.8  580.51 5668.61  611.23 5670.02  616.38 5669.64  630.43 5663.64
  773.96 5664.82     832 5666.84  883.03 5665.98   915.6 5666.63  941.21  5674.4
#Mann= 4 ,-1 , 0
       0     .08       0  151.82     .04       0  215.46     .06       0
  883.03     .08       0
Levee=-1,3.41,5672.46,0,,,,
#XS Ineff= 2 , 0
          104.66 5666.85  456.39         5665.33
Permanent Ineff=
       F       F
Bank Sta=156.19,207.09
XS Rating Curve= 0 ,0
Exp/Cntr=0.5,0.3

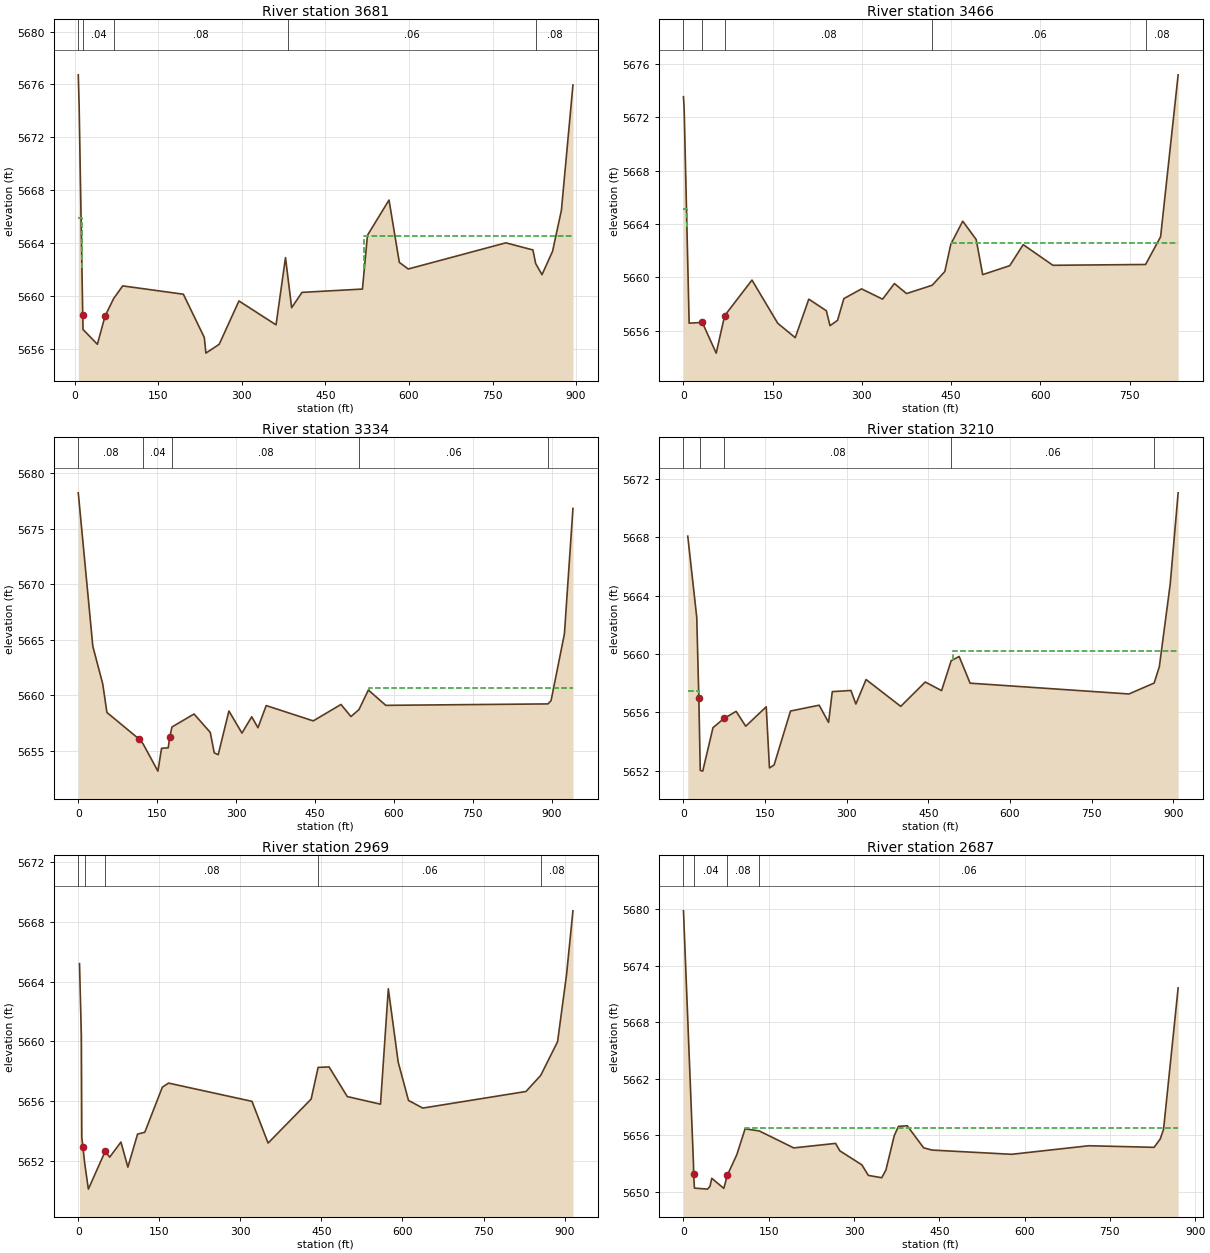
Type RM Length L Ch R = 1 ,3681    ,221.85,214.9,203.15
XS GIS Cut Line= 6
2481156.8098514312072601.5894354      2481145.62     12072561.05
      2481139.15     12072537.66      2481121.12     12072472.35
       2481052.6      12072224.3       2480836.2      12071777.3
#Sta/Elev= 30
    6.34 5676.72    7.93 5674.27   14.34 5658.57   14.89 5657.44   40.65 5656.32
   54.47 5658.46   69.95 5659.79   86.12 5660.74     195 5660.11  232.55 5656.84
  235.45 5655.65  259.37 5656.32  294.78  5659.6  361.39 5657.79  378.34 5662.88
  382.69 5661.39  389.38 5659.09  408.01 5660.25  516.47  5660.5  525.51 5664.57
  564.19 5667.24  582.72 5662.52  598.75 5662.02  773.98    5664  822.54 5663.46
  827.48 5662.43  838.84 5661.59  857.79 5663.36  873.68 5666.47  894.38 5675.95
#Mann= 5 ,-1 , 0
    6.34     .08       0   14.89     .04       0   69.95     .08       0
  382.69     .06       0  827.48     .08       0
#XS Ineff= 2 , 0
       0   12.91 5665.88  519.91       0 5664.49
Permanent Ineff=
       F       F
Bank Sta=14.34,54.47
XS Rating Curve= 0 ,0
Exp/Cntr=0.5,0.3

Type RM Length L Ch R = 1 ,3466    ,129.39,131.37,133.47
XS GIS Cut Line= 6
       2481271.4      12072447.8       2481185.1     12072260.64
      2481179.17     12072247.75      2481169.64     12072227.11
      2481143.16     12072169.65       2480923.2      12071692.6
#Sta/Elev= 30
       0 5673.55    1.14 5672.64    9.55 5656.56   31.66 5656.61   55.03 5654.31
   69.22 5657.12  115.18 5659.79  158.49 5656.55  187.92 5655.47  210.72 5658.36
  240.19 5657.49  246.35 5656.37     259 5656.77  269.63  5658.4  299.44 5659.13
  334.72 5658.36  354.61 5659.53  375.03 5658.78  418.05  5659.4  439.35 5660.43
  449.45 5662.48  469.48 5664.21  492.13 5662.83     503  5660.2  548.51 5660.87
  571.14 5662.45  621.04  5660.9  776.84 5660.96  802.13 5663.04  831.61 5675.19
#Mann= 5 ,-1 , 0
       0     .08       0   31.66     .04       0   69.22     .08       0
  418.05     .06       0  776.84     .08       0
#XS Ineff= 2 , 0
            5.87 5665.15  450.23         5662.56
Permanent Ineff=
       F       F
Bank Sta=31.66,69.22
XS Rating Curve= 0 ,0
Exp/Cntr=0.5,0.3

Type RM Length L Ch R = 1 ,3334    ,124.11,124.29,120.54
XS GIS Cut Line= 6
       2481396.1      12072447.8      2481261.14     12072134.32
      2481261.13     12072134.27       2481214.7     12072026.45
      2481191.22     12071971.88       2481024.4      12071584.4
#Sta/Elev= 30
       0 5678.24   27.67  5664.4   46.49 5661.01   54.44 5658.44  115.35 5656.05
  122.88 5655.63  151.35 5653.15  158.29 5655.21  170.92 5655.25  173.82 5656.21
  178.02 5657.13  220.02  5658.3  250.84 5656.64  258.37  5654.8   265.9 5654.63
  286.27 5658.57  311.06 5656.58  329.61 5658.05  341.44 5657.06   357.1 5659.06
  446.55 5657.68  499.24 5659.16  518.14 5658.07  533.41  5658.7  551.26 5660.46
  584.39 5659.08  892.54 5659.21   898.4  5659.5  923.81 5665.52  940.01 5676.83
#Mann= 5 ,-1 , 0
       0     .08       0  122.88     .04       0  178.02     .08       0
  533.41     .06       0  892.54     .08       0
#XS Ineff= 2 , 0
           28.17 5664.25  551.99          5660.6
Permanent Ineff=
       F       F
Bank Sta=115.35,173.82
XS Rating Curve= 0 ,0
Exp/Cntr=0.5,0.3

Type RM Length L Ch R = 1 ,3210    ,241.1,241.1,239.75
XS GIS Cut Line= 6
       2481471.3      12072327.8      2481386.88     12072137.96
      2481313.16     12071972.22      2481305.66     12071955.33
      2481266.45     12071867.19        2481102.      12071497.4
#Sta/Elev= 30
    7.89 5668.09    24.4 5662.52   28.22 5657.01   30.87 5652.03   35.37 5651.98
   54.24 5654.96   74.51 5655.59   96.72 5656.08  114.36 5655.06  152.03 5656.39
  157.99  5652.2  166.48  5652.4  196.66  5656.1  249.28  5656.5  266.61 5655.32
   273.4 5657.43   307.7 5657.51  316.73 5656.58  335.49 5658.26  399.18 5656.42
  444.15 5658.09  474.22  5657.5  491.84 5659.55   506.5 5659.84   526.6 5658.01
  818.49 5657.27  864.81 5658.02  874.31 5659.15  894.24  5664.8  908.82 5671.06
#Mann= 5 ,-1 , 0
       0     .08       0   30.87     .04       0   74.51     .08       0
  491.84     .06       0  864.81     .08       0
#XS Ineff= 2 , 0
           28.17  5657.5  495.37         5660.22
Permanent Ineff=
       F       F
Bank Sta=28.22,74.51
XS Rating Curve= 0 ,0
Exp/Cntr=0.3,0.1

Type RM Length L Ch R = 1 ,2969    ,282,282.36,275.94
XS GIS Cut Line= 6
       2481643.1      12072151.4      2481374.03     12071635.74
      2481369.19     12071626.49      2481348.29     12071586.41
      2481348.21     12071586.28       2481219.6      12071339.8
#Sta/Elev= 30
    2.28  5665.2    5.69  5660.4    6.55 5653.59    8.57 5652.93   11.76 5651.89
   18.67 5650.12   49.82 5652.65   58.18 5652.26   78.96 5653.27   91.77 5651.59
  109.74  5653.8  123.05 5653.92  155.63 5656.94  167.15 5657.21  321.47 5655.99
  351.27  5653.2  430.94 5656.14  443.88 5658.26  464.19 5658.29  497.82 5656.31
  559.32  5655.8  573.79 5663.52  592.08 5658.61  611.15 5656.05  637.55 5655.54
  828.54 5656.65  855.91 5657.73  887.02 5659.98  903.49 5664.43  915.45 5668.73
#Mann= 5 ,-1 , 0
       0     .08       0   11.76     .04       0   49.82     .08       0
  443.88     .06       0  855.91     .08       0
#XS Ineff= 2 , 0
                          564.81         5658.45
Permanent Ineff=
       F       F
Bank Sta=8.57,49.82
XS Rating Curve= 0 ,0
Exp/Cntr=0.3,0.1

Type RM Length L Ch R = 1 ,2687    ,391.2,393.12,411.84
XS GIS Cut Line= 6
       2481821.9      12071937.3       2481737.2      12071840.8
      2481655.59     12071680.45      2481646.15     12071661.88
      2481642.77     12071655.26       2481400.8      12071179.8
#Sta/Elev= 30
       0 5679.84   17.61 5652.91   17.92 5651.91   19.25 5650.38   42.37 5650.27
   46.66 5650.57   49.76 5651.42   70.99 5650.35    77.1 5651.74   93.77 5653.92
  108.43 5656.68   133.4 5656.45  193.92 5654.65  267.62 5655.13  274.99 5654.34
  313.77 5652.85  325.18 5651.73  348.69 5651.48  356.06 5652.29   370.8 5655.96
  378.18 5656.94  393.62    5657   422.4 5654.66  437.14 5654.42  577.17 5653.97
  713.01 5654.88  827.77 5654.71  838.49 5655.59  844.43 5656.63  870.08 5671.65
#Mann= 4 ,-1 , 0
       0     .08       0   19.25     .04       0    77.1     .08       0
   133.4     .06       0
#XS Ineff= 2 , 0
                          108.84         5656.75
Permanent Ineff=
       F       F
Bank Sta=17.92,77.1
XS Rating Curve= 0 ,0
Exp/Cntr=0.3,0.1

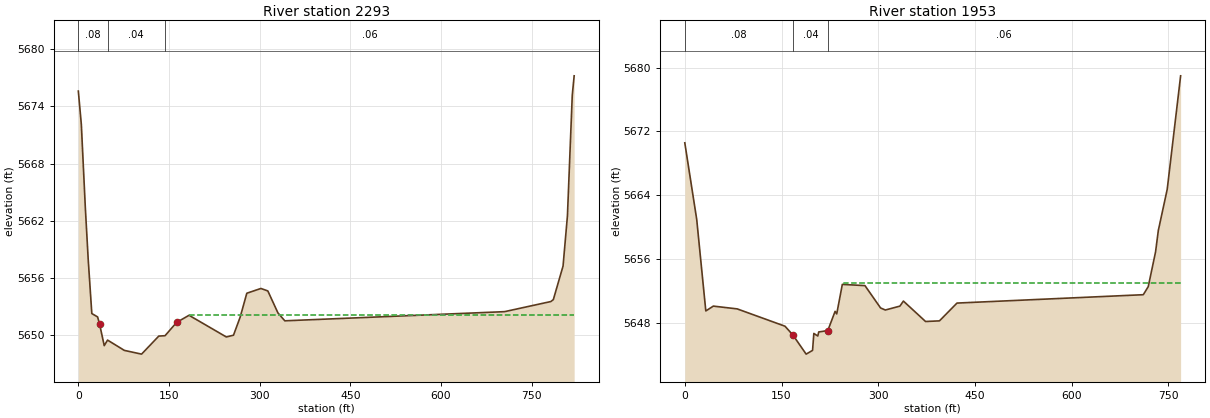
Type RM Length L Ch R = 1 ,2293    ,325.29,339.92,346.64
XS GIS Cut Line= 6
       2482066.5      12071645.6       2481960.6      12071504.4
      2481705.84     12071013.11      2481700.25     12071002.31
      2481693.47     12070989.26       2481664.2      12070932.8
#Sta/Elev= 30
       0  5675.6    4.97 5672.11   11.62 5663.33   16.34 5657.96   22.31 5652.29
   31.87 5651.94   35.14 5651.19   42.86 5648.93   48.38 5649.51   76.16 5648.43
  104.64 5648.04  133.11 5649.93  143.46 5649.97  162.59 5651.36  183.16 5652.11
  244.84 5649.84   256.7 5650.02  267.75 5651.91  278.76 5654.42  302.11 5654.92
  313.57 5654.66  330.24 5652.36  341.64 5651.53   705.3 5652.49   781.8 5653.55
  785.92 5653.75  802.01 5657.27  809.26 5662.53  817.27 5675.18  820.38  5677.2
#Mann= 3 ,-1 , 0
       0     .08       0   48.38     .04       0  143.46     .06       0
#XS Ineff= 2 , 0
                           182.7         5652.17
Permanent Ineff=
       F       F
Bank Sta=35.14,162.59
XS Rating Curve= 0 ,0
Exp/Cntr=0.3,0.1

Type RM Length L Ch R = 1 ,1953    ,0,0,0
XS GIS Cut Line= 6
       2482266.5      12071450.3      2482263.33     12071443.77
      2482247.14     12071410.51      2482204.07     12071321.94
      2482144.26       12071199.       2481930.1      12070758.7
#Sta/Elev= 30
       0 5670.56   18.47 5660.97   32.59 5649.48   44.25 5650.09   81.31 5649.74
  155.41 5647.57  167.74 5646.46  188.21 5644.07  198.17 5644.54  200.16 5646.66
  206.29 5646.34  207.76 5646.85  221.81 5647.02  233.11 5649.43  235.67 5649.11
  244.34 5652.81  279.45 5652.66  303.63 5649.86  311.04  5649.6   333.7 5650.09
  339.08 5650.72  373.46 5648.16     395 5648.24   422.2 5650.47  711.21 5651.52
  718.89 5652.54  730.19 5656.88  734.48 5659.57  748.27 5664.73  769.07 5678.96
#Mann= 3 , 0 , 0
       0     .08       0  167.74     .04       0  221.81     .06       0
#XS Ineff= 2 , 0
                           246.3         5652.94
Permanent Ineff=
       F       F
Bank Sta=167.74,221.81
XS Rating Curve= 0 ,0
Exp/Cntr=0.3,0.1

Chan Stop Cuts=-1
Use User Specified Reach Order=0
Composite Channel Slope=5